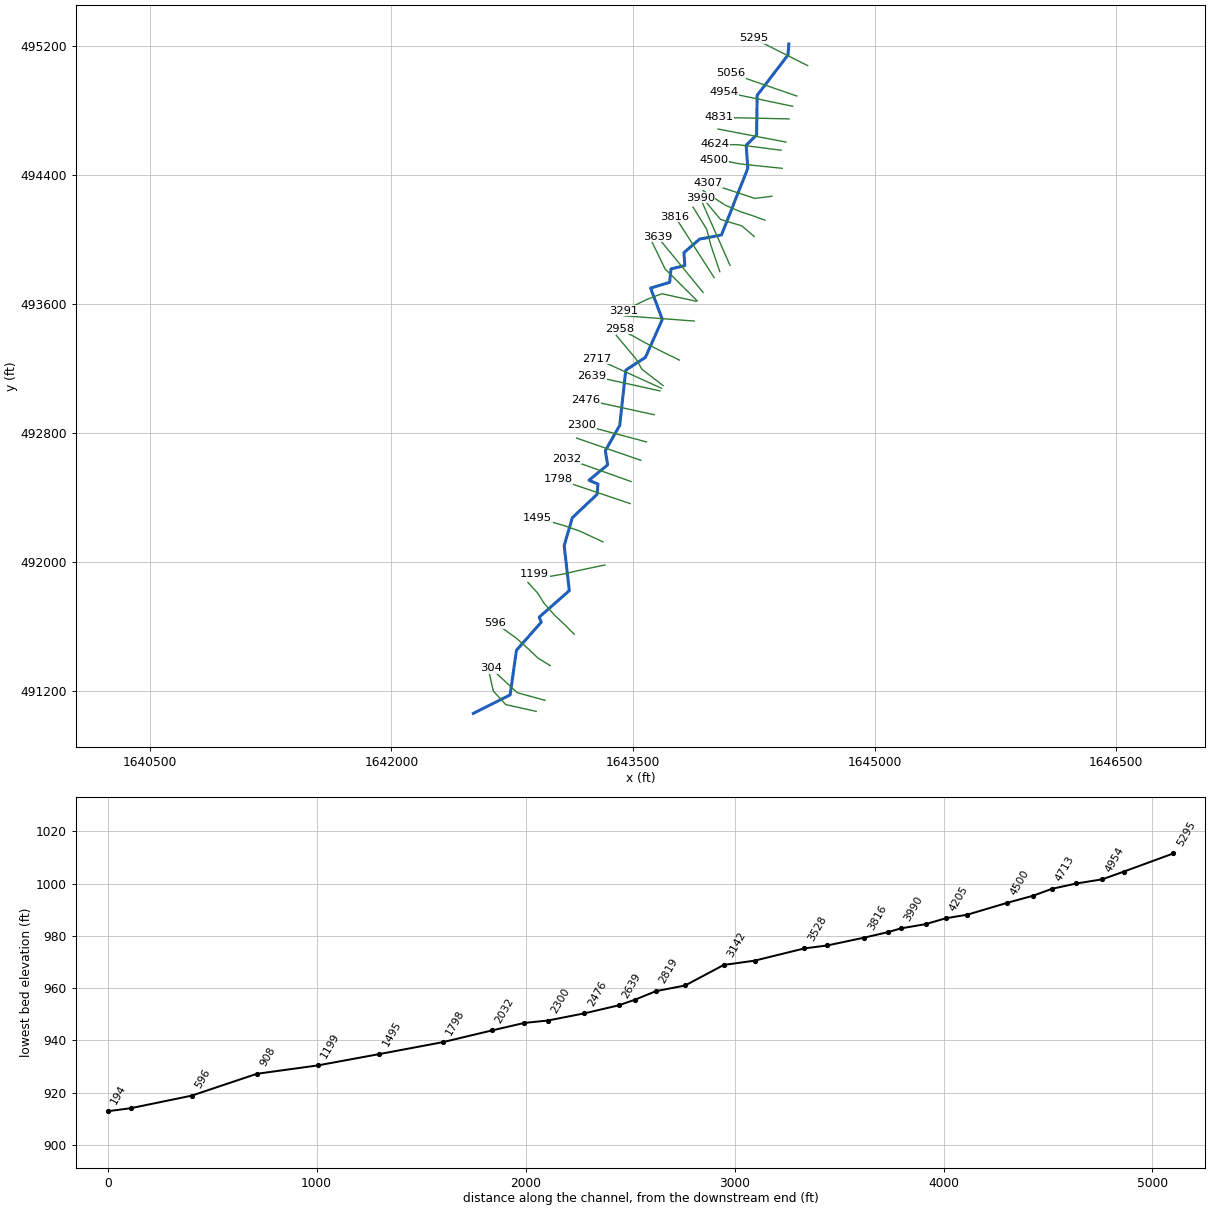
--- LickRn.prj (project) ---

Proj Title=LickRn
Current Plan=p01
Default Exp/Contr=0,0
English Units
Geom File=g01
Flow File=f01
Plan File=p01
BEGIN DESCRIPTION:
---------- MODELED AS PART OF WVEM CTP PROGRAM, 2025----------
Stream Name: Lick Run
Flood Zone: AFH
Marshall County, WV
HEC-RAS Version: RAS 6.6
Vertical Datum: NAVD88
Projection: NAD 1983 StatePlane West Virginia N FIPS 4701 (US Feet)
Terrain: 1-meter West Virginia FEMA R3 South Central (collected 2018-2019)
Land Use: 2024 NLCD
Hydrologic Method:
Duda et al., "Estimation of magnitude and frequency of floods for rural, unregulated streams in and near Virginia and West Virginia." September 8, 2025.
Additional Model Notes:
None
END DESCRIPTION:
DSS Export Rating Curves= 0
DSS Export Rating Curve Sorted= 0
DSS Export Volume Flow Curves= 0
DXF OffsetX= 0
DXF OffsetY= 0
DXF ScaleX= 0
DXF ScaleY= 0

--- LickRn.p01 (plan) ---

Plan Title=Floodplain
Program Version=6.60
Short Identifier=Floodplain
Geom File=g01
Flow File=f01
Subcritical Flow
K Sum by GR= 0
Std Step Tol= 0.01
Critical Tol= 0.01
Num of Std Step Trials= 20
Max Error Tol= 0.3
Flow Tol Ratio= 0.001
Split Flow NTrial= 30
Split Flow Tol= 0.02
Split Flow Ratio= 0.02
Log Output Level= 0
Friction Slope Method= 1
Unsteady Friction Slope Method= 2
Unsteady Bridges Friction Slope Method= 1
Parabolic Critical Depth
Global Vel Dist= 0 , 0 , 0
Global Log Level= 0
CheckData=False
Encroach Param=-1 ,0,0, 0
Flow Ratio Tolerance=0.1
Flow Ratio Min Ratio=0.5
Flow Ratio Max Ratio=4
Flow Ratio Max Iterations= 10
Mapping Interval=1HOUR
Computation Time Step Use Courant=        0
Computation Time Step Use Time Series=    0
Computation Time Step Count To Double=0
Computation Time Step Max Doubling=0
Computation Time Step Max Halving=0
Computation Time Step Residence Courant=0
Run HTab= 0
Run UNet= 0
Run Sediment= 0
Run PostProcess= 0
Run WQNet= 0
Run RASMapper=-1
UNET Theta= 0
UNET Theta Warmup= 0
UNET ZTol= 0
UNET ZSATol= 0
UNET MxIter= 0
UNET Max Iter WO Improvement= 0
UNET MaxInSteps= 0
UNET DtIC= 0
UNET DtMin= 0
UNET MaxCRTS= 0
UNET WFStab= 0
UNET SFStab= 0
UNET WFX= 1
UNET SFX= 1
UNET Gravity=32.17405
UNET 1D Methodology=Finite Difference
UNET DSS MLevel= 1
UNET Pardiso=0
UNET DZMax Abort= 0
UNET Use Existing IB Tables= 0
UNET Froude Reduction=False
UNET Froude Limit= 0
UNET Froude Power= 0
UNET D1 Cores= 0
UNET WindReference=Eulerian
UNET WindDragFormulation=Hsu (1988)
UNET D2 Coriolis=0
UNET D2 Cores= 0
UNET D2 Theta= 1
UNET D2 Theta Warmup= 1
UNET D2 Z Tol= 0.01
UNET D2 Volume Tol= 0.01
UNET D2 Max Iterations= 20
UNET D2 Advanced Convergence=0
UNET D2 WS Max Tol=0.15
UNET D2 WS RMS Tol=0.002
UNET D2 WS Stall Tol=1
UNET D2 Equation= 0
UNET D2 RampUpFraction=0.1
UNET D2 TimeSlices= 1
UNET D2 Turbulence Formulation=Non-Conservative (original)
UNET D2 Eddy Viscosity=0.3
UNET D2 Transverse Eddy Viscosity=0.1
UNET D2 Smagorinsky Mixing=0
UNET D2 BCVolumeCheck=0
UNET D2 Cores=0
UNET D2 SolverType=PARDISO (Direct)
UNET D2 Minimum Iterations= 3
UNET D2 Maximum Iterations= 30
UNET D2 Restart Number= 10
UNET D2 Relaxation Coeff=1.3
UNET D2 SOR Precondition Iterations= 10
UNET D2 ILUT Maximum Fill= 8
UNET D2 ILUT Tolerance=1E-08
UNET D2 Convergence Tolerance=0.00001
PS Theta= 1
PS WS Tol= 0.01
PS Volume Tol= 0.01
PS Max Iterations= 20
PS Equation= 0
PS Advance Time Step=-1
PS Target Courant=0.9
PS Time Slices= 1
PS Iterate With 2D=0
PS Project Initial WSE from DS=-1
PS Ramp Up Initial WSE from US=-1
PS Cores=0
UNET D1D2 MaxIter= 0
UNET D1D2 ZTol=0.01
UNET D1D2 QTol=0.1
UNET D1D2 MinQTol=1
Write IC File= 0
Write IC File at Fixed DateTime=0
Write IC File at Sim End=0
Echo Input=False
Echo Parameters=False
Echo Output=False
Write Detailed= 0
HDF Write Warmup=0
HDF Write Time Slices=0
HDF Flush=0
HDF Compression= 1
HDF Chunk Size= 1
HDF Spatial Parts= 1
HDF Use Max Rows=0
HDF Fixed Rows= 1
Calibration Method= 0
Calibration Iterations= 20
Calibration Max Change=0.05
Calibration Tolerance=0.2
Calibration Maximum=1.5
Calibration Minimum=0.5
Calibration Optimization Method= 1
WQ AD Non Conservative
WQ ULTIMATE=-1
WQ Max Comp Step=1HOUR
WQ Output Interval=15MIN
WQ Output Selected Increments= 0
WQ Create Restart=0
WQ Fixed Restart=0
WQ System Summary=0
WQ Write To DSS=0
Sorting and Armoring Iterations= 10
XS Update Threshold= 0.02
Bed Roughness Predictor= 0
Processes Affected by Predictor=Sediment Only
Hydraulics Update Threshold= 0.02
Energy Slope Method= 1
Volume Change Method= 1
Sediment Retention Method= 0
Sediment TS Multiplier= 1
Warm Up Method= 0
XS Weighting Method= 0
Number of US Weighted Cross Sections= 1
Number of DS Weighted Cross Sections= 1
Upstream XS Weight=0
Main XS Weight=1
Downstream XS Weight=0
Number of DS XS's Weighted with US Boundary= 1
Upstream Boundary Weight= 1
Weight of XSs Associated with US Boundary= 0
Number of US XS's Weighted with DS Boundary= 1
Downstream Boundary Weight= 0.5
Weight of XSs Associated with DS Boundary= 0.5
Percentile Method= 0
Sediment Output Level= 3
Mass or Volume Output= 0
Output Increment Type= 1
Profile and TS Output Increment= 1
Transport Output Increment 1
XS Output Flag= 0
XS Output Increment= 10
Read HDF5 Sediment Hotstart= 0
Sediment Hotstart Type= 0
Write Gradation File= 0
Read Gradation Hotstart= 0
Write HDF5 File= 1
Write Binary Output= 1
Write DSS Sediment File= 0
DSS Sediment Output Type= 1
SV Curve= 0
Specific Gage Flag= 0
Subcell Erosion Methods= 0
Subcell Deposition Methods= 0
Advection Scheme= 1
Matrix Solver= 0
Implicit Weighting Factor= 1
Maximum Outer Loop Convergence Iterations= 5
Convergence Maximum Absolute= 0.001
Convergence RMSE= 0.0001
Grain Fractions Max Abs Error= 0.001
Max Subgrid Regions= 1
Max Subgrid Length Scale= 3.402823E+38
Initial Layer Thickness= 3
Min Layer Thickness= 0.1
Max Layer Thickness= 6
Number of Layers= 5

--- LickRn.f01 (steady flow) ---

Flow Title=Flow
Program Version=6.60
Number of Profiles= 1
Profile Names=P100yr
River Rch & RM=LickRn,Main            ,5295
     773
Boundary for River Rch & Prof#=LickRn,Main            , 1
Up Type= 0
Dn Type= 3
Dn Slope=0.023643
DSS Import GetInterval= 0
DSS Import GetPeak= 0
DSS Import FillOption= 0

--- LickRn.g01 (geometry) ---

Geom Title=Geometry
Program Version=6.60

River Reach=LickRn          ,Main
Reach XY= 30
     1644467.264      495214.237     1644462.342      495146.173
     1644270.536      494894.678     1644267.338      494649.662
     1644202.541      494584.865     1644212.679      494442.521
     1644049.186      494028.189     1643913.297      494002.375
     1643815.992      493918.495       1643821.7      493838.587
     1643735.956      493817.655     1643727.242      493734.007
     1643609.375      493698.255     1643681.945      493503.629
     1643576.985      493268.624     1643454.977      493188.991
     1643417.532       492846.21      1643328.07      492688.949
      1643342.71      492601.113      1643226.45      492505.348
     1643282.133      492481.495     1643277.263      492418.184
     1643123.423      492273.039     1643072.614      492099.985
     1643104.457      491819.928      1642917.49      491655.395
     1642930.553      491624.711     1642776.279      491449.659
     1642737.211      491173.072     1642509.049      491058.085

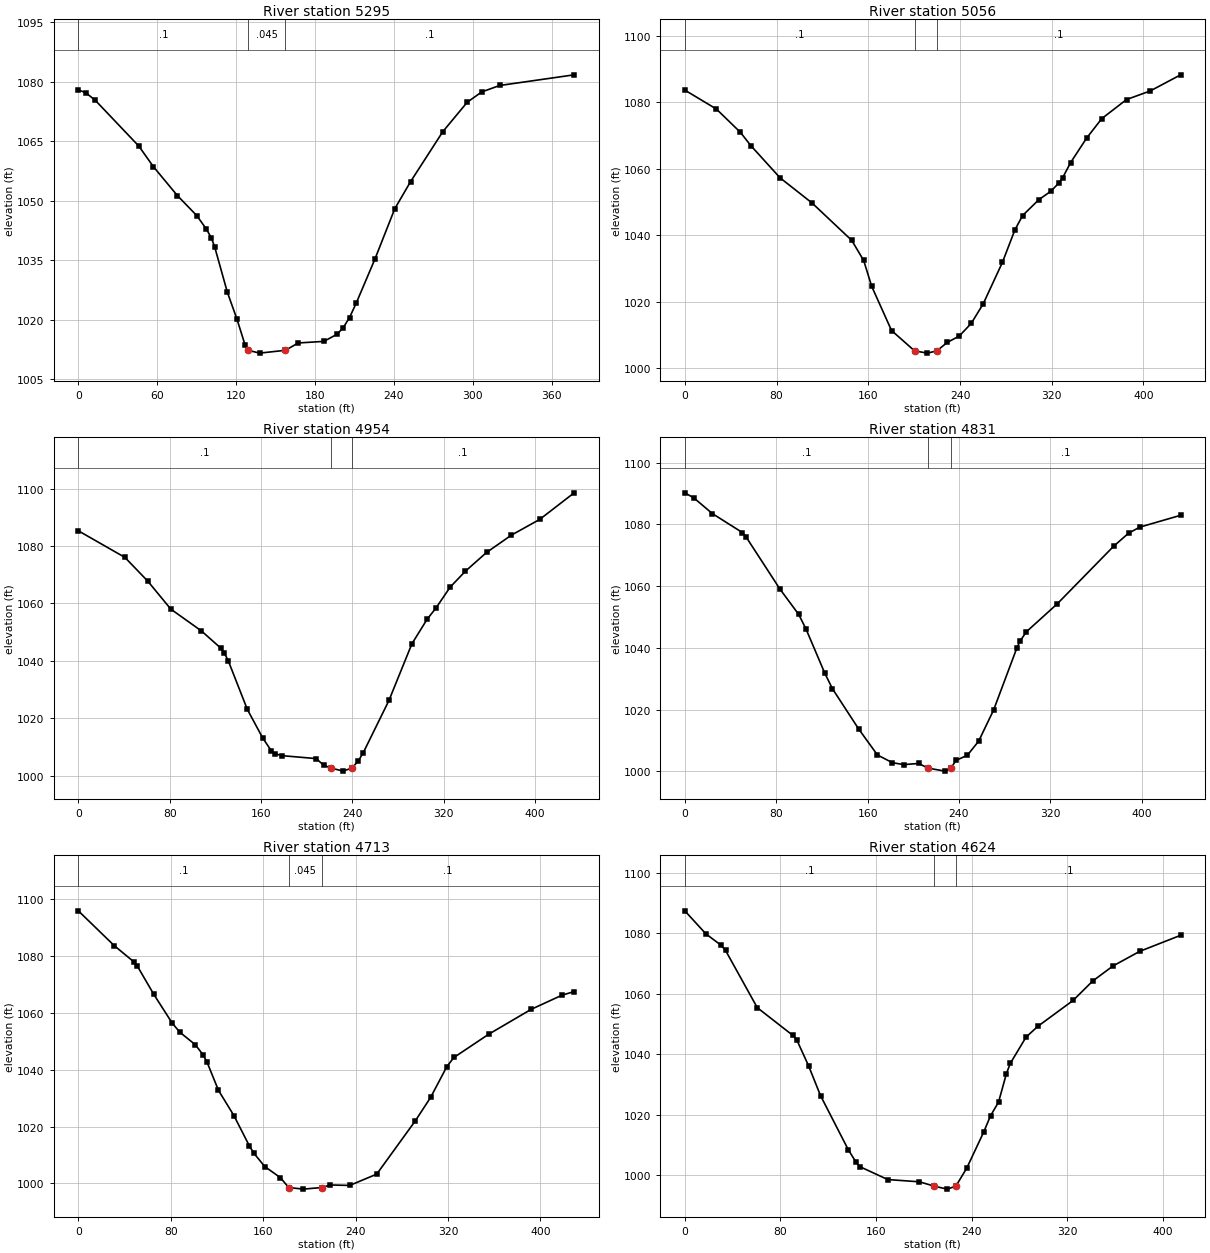
Type RM Length L Ch R = 1 ,5295    ,236.3,238.8,236.5
XS GIS Cut Line= 2
1644584.37381547495079.6024961071644247.50729474495248.972535171
#Sta/Elev= 30
       0 1077.91     5.6 1077.23      13 1075.26      46 1063.75      57  1058.6
    75.4 1051.25    90.1 1046.22    97.4 1042.81   101.1 1040.64   103.6 1038.43
   113.3 1026.92   120.7 1020.05   126.8  1013.6  129.211012.286   137.8 1011.57
  157.441012.285   167.2 1014.13   186.7 1014.53   196.6 1016.31   201.3 1017.93
   206.2 1020.54   211.3 1024.18   225.4 1035.19   240.6 1047.96   252.6 1054.79
   277.1 1067.38   295.7 1074.81   306.7  1077.4   320.3 1079.03     377 1081.72
#Mann= 3 ,-1,0
       0      .1       0  129.21    .045       0  157.44      .1       0
Bank Sta=129.21,157.44
XS Rating Curve= 0 ,0
Exp/Cntr=0.3,0.1

Type RM Length L Ch R = 1 ,5056    ,100.5,102.3,102.7
XS GIS Cut Line= 2
 1644516.8289445494890.6801357571644108.18981805495032.077576829
#Sta/Elev= 30
       0 1083.67    27.6 1077.96    48.4    1071    57.7 1066.93    83.1 1057.28
   110.9 1049.74   145.6 1038.47     156 1032.43     163 1024.64   180.3 1011.37
  200.38 1005.25   211.6 1004.57  219.871005.251   228.9  1007.8   239.3 1009.69
   249.8 1013.51   260.2 1019.37     277 1031.87   287.9 1041.66   294.6 1045.95
   308.8 1050.73   319.2 1053.24     326 1055.65   329.6 1057.37   336.5 1061.89
   350.4 1069.22   363.6 1075.08   385.2 1080.82     406 1083.43   432.4 1088.26
#Mann= 3 ,-1,0
       0      .1       0  200.38    .045       0  219.87      .1       0
Bank Sta=200.38,219.87
XS Rating Curve= 0 ,0
Exp/Cntr(USF)=0,0
Exp/Cntr=0.3,0.1

Type RM Length L Ch R = 1 ,4954    ,120.8,123,124.4
XS GIS Cut Line= 2
1644491.29875068494827.2212547451644066.27094624494915.915073441
#Sta/Elev= 30
       0 1085.29    40.8 1076.02    60.9 1067.72      81 1058.02   107.8 1050.43
   124.5 1044.54   127.9  1042.7   131.2 1040.14     148 1023.11   161.4 1013.23
     169 1008.71   171.8 1007.75   178.2 1007.03   208.3    1006     215 1003.65
  221.091002.741   231.8 1001.64  239.721002.741   245.2 1005.23   249.4 1007.96
     272 1026.23   292.1 1045.95   305.5 1054.54   313.2 1058.41   325.6 1065.67
     339 1071.24   357.5 1077.75   379.3 1083.79     404 1089.24   434.2  1098.5
#Mann= 3 ,-1,0
       0      .1       0  221.09    .045       0  239.72      .1       0
Bank Sta=221.09,239.72
XS Rating Curve= 0 ,0
Exp/Cntr(USF)=0,0
Exp/Cntr=0.3,0.1

Type RM Length L Ch R = 1 ,4831    ,117.2,118,110.7
XS GIS Cut Line= 2
1644469.03761859494748.7632497811644035.14043228494758.010238997
#Sta/Elev= 30
       0 1090.25     7.8 1088.64    24.2  1083.5    50.5 1077.36    53.7 1075.92
    83.3 1059.05    99.7 1050.85   106.2 1046.03   122.6 1031.75   129.2 1026.79
   152.2 1013.72   168.6 1005.31   181.7 1002.81   191.6 1002.18   204.7 1002.55
  212.871001.044   227.7 1000.07  232.811001.042   237.5 1003.57   247.3  1005.2
   257.2 1009.77   270.3 1019.88   290.6 1039.92   293.3 1042.13     299 1045.22
   326.1 1054.31   375.3 1072.92   388.5 1077.19   398.3 1079.14     434 1082.97
#Mann= 3 ,-1,0
       0      .1       0  212.87    .045       0  232.81      .1       0
Bank Sta=212.87,232.81
XS Rating Curve= 0 ,0
Exp/Cntr(USF)=0,0
Exp/Cntr=0.3,0.1

Type RM Length L Ch R = 1 ,4713    ,84.5,88.2,79.9
XS GIS Cut Line= 2
1644449.14723288494605.0476296951644027.63205492494685.838038804
#Sta/Elev= 30
       0 1095.82    31.1 1083.58    47.8 1077.98    51.2 1076.31    65.3 1066.48
    81.2 1056.39    87.9 1053.14   101.3 1048.75   107.9 1045.25   111.3 1042.75
   121.3 1032.73   134.7 1023.84     148 1013.25   152.1 1010.55   161.4 1005.94
   174.8 1002.08  182.13998.5771   194.8  998.01  210.69 998.577   218.2  999.47
   234.9  999.31   258.3 1003.28   291.7 1022.01     305 1030.28     319 1041.08
   325.1 1044.28   355.1 1052.42   391.9 1061.18   418.6 1066.16   429.2 1067.44
#Mann= 3 ,-1,0
       0      .1       0  182.13    .045       0  210.69      .1       0
Bank Sta=182.13,210.69
XS Rating Curve= 0 ,0
Exp/Cntr(USF)=0,0
Exp/Cntr=0.3,0.1

Type RM Length L Ch R = 1 ,4624    ,124.5,124.4,124.4
XS GIS Cut Line= 3
1644419.64130868494554.2603398491644154.87708752494588.245001073
1644007.08332824494590.616023949
#Sta/Elev= 30
       0 1087.43    17.6 1079.83    30.2 1076.09    34.1 1074.32    60.6 1055.42
    90.4 1046.23    93.7 1044.71   103.5 1036.22   113.5 1026.34   136.7 1008.47
   143.3 1004.26   146.6 1002.81   169.7  998.58   196.2  997.83  208.71996.3939
   219.4  995.41  226.74996.3951   235.9 1002.42   250.1 1014.37   255.7 1019.66
   262.4 1024.17     269  1033.6   272.2 1036.95   285.4 1045.66   295.2 1049.22
   324.7 1057.78   341.2 1064.23   358.1 1069.19   380.5 1074.03   414.7 1079.34
#Mann= 3 ,-1,0
       0      .1       0  208.71    .045       0  226.74      .1       0
Bank Sta=208.71,226.74
XS Rating Curve= 0 ,0
Exp/Cntr(USF)=0,0
Exp/Cntr=0.3,0.1

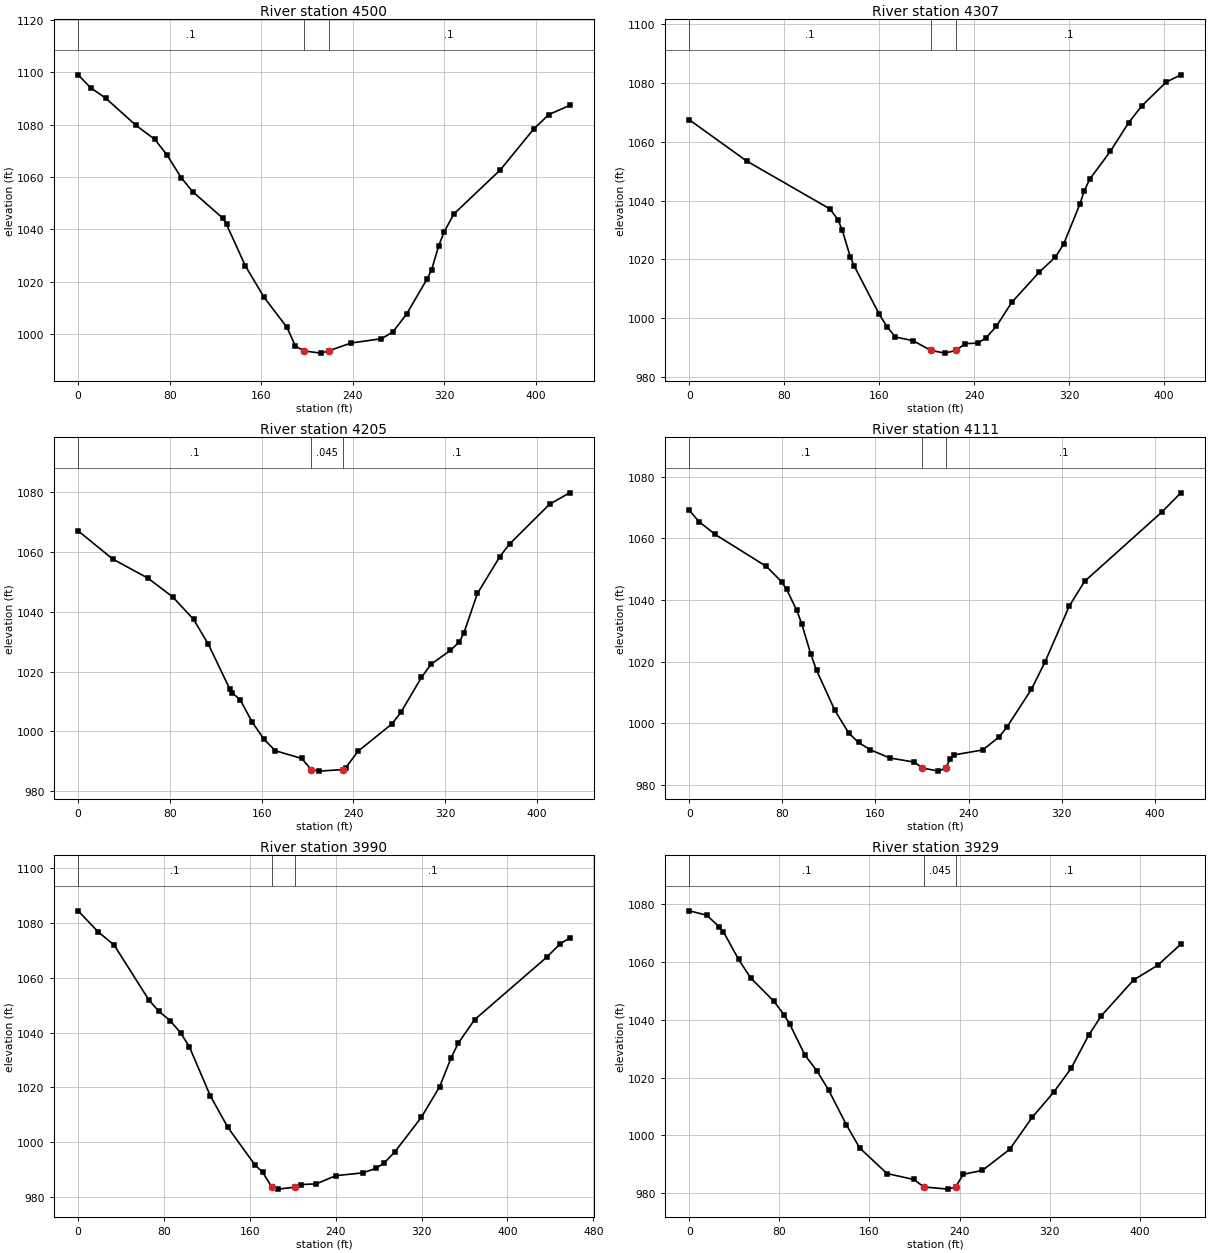
Type RM Length L Ch R = 1 ,4500    ,192.6,192.6,188.8
XS GIS Cut Line= 6
1644426.24349576494442.0301144271644339.18264626494450.865398586
1644264.57485583494458.5336903331644165.15412292494469.281700343
1644090.98169909494484.1550301761644000.31193292494496.032959178
#Sta/Elev= 30
       0 1099.07      11  1094.1    24.2 1090.12    50.6 1079.73      67 1074.42
    77.6  1068.5    90.1 1059.75     100 1054.45   126.4 1044.29   129.7 1041.89
   146.2 1026.01   162.5 1014.04   182.5 1002.53   189.9   995.4  197.29993.5395
   212.2  992.68  219.02993.5385   238.6  996.56     265  998.16   275.1 1000.78
   287.1 1007.61   305.2 1021.17   308.9 1024.45   315.2 1033.78     320 1039.11
   328.4 1045.87   368.9 1062.69   398.1 1078.31   411.4 1083.89   429.6 1087.37
#Mann= 3 ,-1,0
       0      .1       0  197.29    .045       0  219.02      .1       0
Bank Sta=197.29,219.02
XS Rating Curve= 0 ,0
Exp/Cntr(USF)=0,0
Exp/Cntr=0.3,0.1

Type RM Length L Ch R = 1 ,4307    ,103.3,102.7,101.4
XS GIS Cut Line= 3
1644361.63028231494268.6311173821644256.35686661494255.116286989
  1643964.009746494351.854020331
#Sta/Elev= 30
       0 1067.47    48.4 1053.43   118.4 1037.17   125.3 1033.48   128.8 1029.97
   135.7 1020.75   139.1 1017.59   159.9 1001.41   166.8  996.93   173.7  993.57
   188.5  992.34  203.41989.0495   215.2   988.1  224.84989.0502   232.4  991.34
   242.8   991.5   249.7   993.2   258.6  997.19   271.6 1005.34   294.6 1015.55
   308.5 1020.83   315.4 1025.23   329.2 1038.94   332.7 1043.37   337.6 1047.42
   354.7 1056.74   370.2 1066.52     381 1072.11   401.8 1080.31   414.1 1082.77
#Mann= 3 ,-1,0
       0      .1       0  203.41    .045       0  224.84      .1       0
Bank Sta=203.41,224.84
XS Rating Curve= 0 ,0
Exp/Cntr(USF)=0,0
Exp/Cntr=0.3,0.1

Type RM Length L Ch R = 1 ,4205    ,92.3,94.1,92.9
XS GIS Cut Line= 6
1644318.97238484494120.0668475931644236.60772017494149.898152754
1644165.29487067494173.2350483391644073.29243001494212.792712003
1644009.14918558494254.5895444151643934.83273317494303.658343926
#Sta/Elev= 30
       0 1067.05    30.1 1057.64    60.9 1051.22    82.5 1044.94   100.6 1037.48
   113.6 1029.09   132.2 1014.17   134.3 1012.88   141.2 1010.63   151.6 1003.22
   161.9  997.45   171.9  993.56   194.9  990.98  203.16987.2624   209.9  986.75
  230.95987.2625   233.3  987.92     244  993.39   273.6 1002.56   281.4 1006.44
   299.2 1018.04   307.4 1022.41   324.5 1027.11   332.3 1029.95   336.2 1032.88
     348 1046.11   367.6 1058.45   376.1 1062.67   410.9 1075.93   428.4 1079.75
#Mann= 3 ,-1,0
       0      .1       0  203.16    .045       0  230.95      .1       0
Bank Sta=203.16,230.95
XS Rating Curve= 0 ,0
Exp/Cntr(USF)=0,0
Exp/Cntr=0.3,0.1

Type RM Length L Ch R = 1 ,4111    ,125.8,121,107
XS GIS Cut Line= 4
1644252.43083435494018.8127966661644176.24986934494084.110766673
1644043.09322462494125.0820419711643925.94098432494265.280624631
#Sta/Elev= 30
       0 1069.08     8.2 1065.45    22.2 1061.27    66.3 1050.87    79.3 1045.94
    83.6 1043.46    92.3 1036.66    96.6 1032.32   104.2 1022.66   109.3 1017.26
   125.1  1004.2     137  996.88   145.4  993.82   155.7  991.42   172.3  988.79
   193.5  987.45  200.07985.5545   214.1  984.53  220.31 985.554   224.4  988.56
   227.8  989.81   252.1  991.39   266.1  995.56   273.1   998.9     294 1011.06
   305.7 1019.94   326.6 1038.09   339.7 1046.05   406.2 1068.56   422.4 1074.75
#Mann= 3 ,-1,0
       0      .1       0  200.07    .045       0  220.31      .1       0
Bank Sta=200.07,220.31
XS Rating Curve= 0 ,0
Exp/Cntr(USF)=0,0
Exp/Cntr=0.3,0.1

Type RM Length L Ch R = 1 ,3990    ,56,60.2,54
XS GIS Cut Line= 2
1644102.29293082493839.2950563981643917.35314649494258.175764497
#Sta/Elev= 30
       0 1084.39    18.6 1076.74    33.6 1071.88    65.9 1051.88      75  1047.8
    85.8 1044.31    95.8 1039.71   103.7 1034.72   123.1 1016.95   139.5 1005.38
   164.6  991.76   171.8  989.06  180.49983.5834   186.2  982.86  202.22983.5847
   207.7  984.53     222  984.78   239.9  987.77     265  988.78   277.4  990.43
   284.9  992.34   294.8  996.33   319.7 1009.03   336.8 1020.23   347.5 1030.78
   354.1  1036.1   369.4  1044.7   436.6 1067.49   449.1 1072.37   457.9 1074.45
#Mann= 3 ,-1,0
       0      .1       0  180.49    .045       0  202.22      .1       0
Bank Sta=180.49,202.22
XS Rating Curve= 0 ,0
Exp/Cntr(USF)=0,0
Exp/Cntr=0.3,0.1

Type RM Length L Ch R = 1 ,3929    ,108.7,113.8,115.7
XS GIS Cut Line= 4
1644038.75843756493800.5472938211643983.70328638493963.223173346
1643957.24928284494063.9265711341643872.88167715494200.728534839
#Sta/Elev= 30
       0 1077.62    15.4 1076.12    26.7 1072.06    30.2 1070.44    43.8 1060.82
    54.4 1054.48    74.9 1046.47    84.2 1041.68    89.1 1038.54   102.9 1027.65
   113.3 1022.36   123.7 1015.72   139.6 1003.62   151.4  995.65   175.6  986.85
   199.3  984.79  208.42  982.21   229.9  981.46   236.6  982.21   243.4   986.6
   260.4  987.94   284.5  995.18   304.5 1006.22   323.8 1015.01   339.2 1023.23
   354.6 1034.56     366 1041.37   394.6 1053.71   416.1 1058.83   436.6 1066.09
#Mann= 3 ,-1,0
       0      .1       0  208.42    .045       0   236.6      .1       0
Bank Sta=208.42,236.6
XS Rating Curve= 0 ,0
Exp/Cntr(USF)=0,0
Exp/Cntr=0.3,0.1

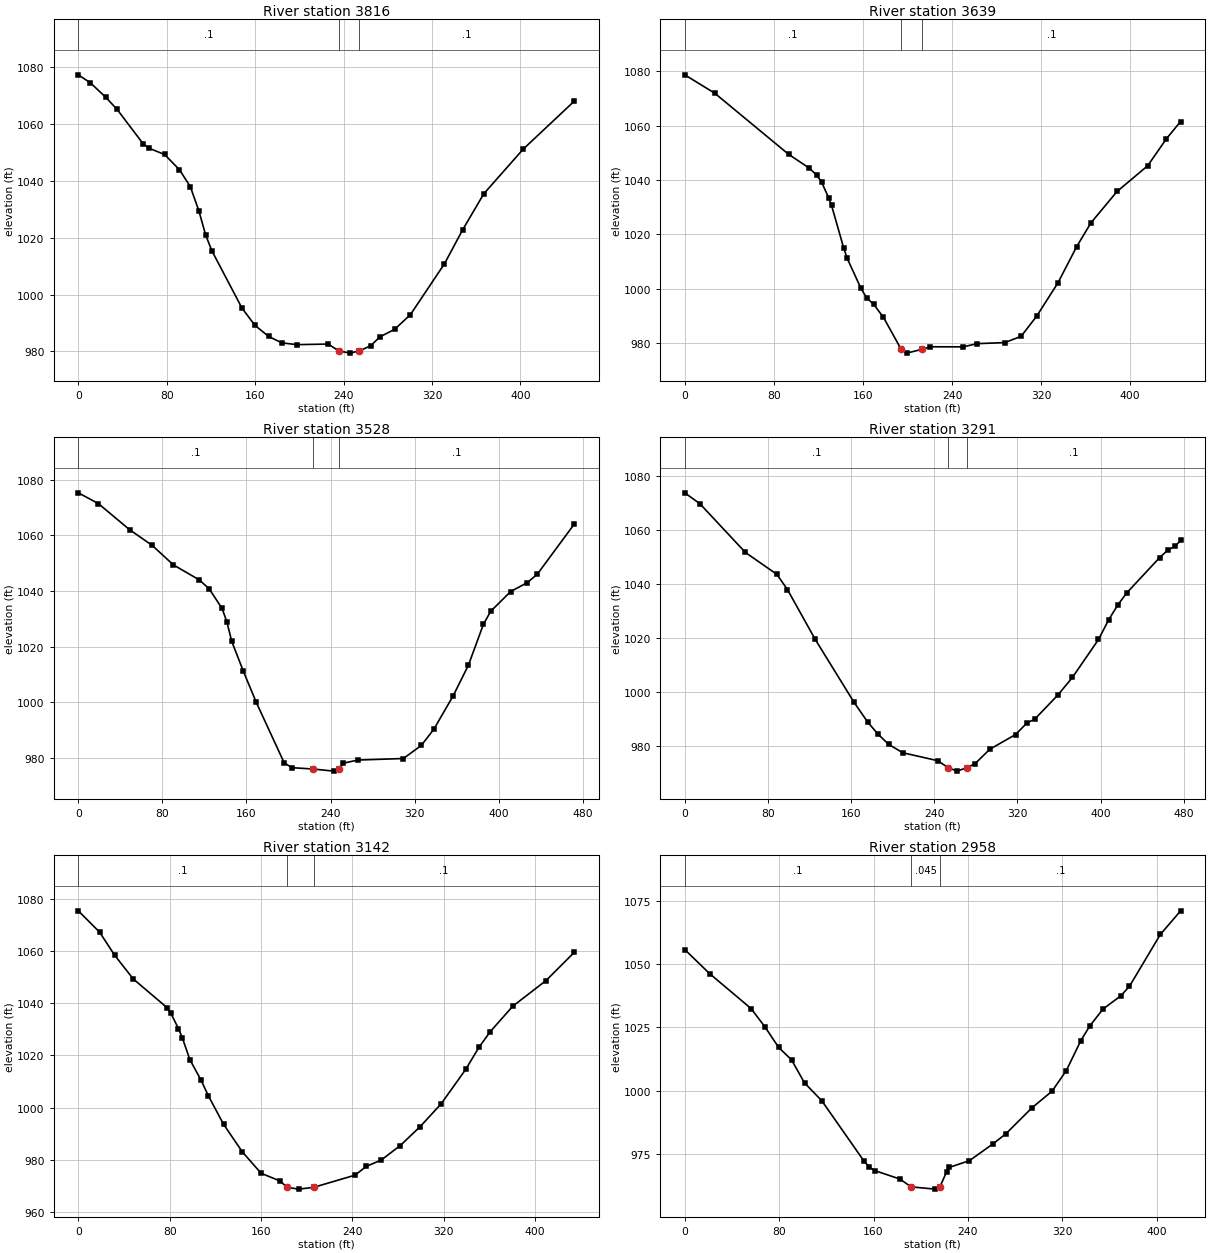
Type RM Length L Ch R = 1 ,3816    ,173,176.5,173.1
XS GIS Cut Line= 2
1644003.69339766493763.5346738611643761.34144385494141.208321846
#Sta/Elev= 30
       0  1077.4    10.8 1074.62      25 1069.42    35.1 1065.21    58.5 1053.18
      64 1051.54      78 1049.34    91.5 1043.97   101.3 1038.05   109.1 1029.44
   115.2 1021.01   120.8 1015.44   148.1   995.2   159.8  989.15   172.2  985.23
   184.1  982.97   197.7  982.34   226.1  982.54  235.73980.1415   245.8  979.35
  254.17980.1411   264.5  981.91   272.9  985.08   286.2  987.72   300.5  992.89
   331.3 1010.81   347.9 1022.87   366.9 1035.48   402.6 1051.22   448.7 1068.09
#Mann= 3 ,-1,0
       0      .1       0  235.73    .045       0  254.17      .1       0
Bank Sta=235.73,254.17
XS Rating Curve= 0 ,0
Exp/Cntr(USF)=0,0
Exp/Cntr=0.3,0.1

Type RM Length L Ch R = 1 ,3639    ,108.4,110.9,105.8
XS GIS Cut Line= 2
1643934.90763559493671.8007516511643652.51881105494016.073273253
#Sta/Elev= 30
       0 1078.67    26.9 1071.91    93.2 1049.46   111.6 1044.42   118.6 1041.76
   122.9 1039.19   129.4 1033.27   131.8 1030.65   142.6 1015.16   145.8 1011.25
   158.1 1000.25   163.3  996.68   169.6  994.31   178.4  989.52  194.29 977.787
   199.3  976.36   213.4  977.79   220.5  978.69   250.2  978.67   262.3  979.84
   287.5  980.24     302  982.53   315.9  989.88     335 1002.11     352 1015.54
   364.7 1024.23   388.2 1035.78   415.7 1045.24   432.6  1055.2   445.3 1061.51
#Mann= 3 ,-1,0
       0      .1       0  194.29    .045       0   213.4      .1       0
Bank Sta=194.29,213.4
XS Rating Curve= 0 ,0
Exp/Cntr(USF)=0,0
Exp/Cntr=0.3,0.1

Type RM Length L Ch R = 1 ,3528    ,219.5,237.7,246.1
XS GIS Cut Line= 3
1643898.75541496493618.8389792081643699.21904189493817.165509555
1643616.23691368493988.647819087
#Sta/Elev= 30
       0 1075.35    19.1 1071.47    48.8 1062.08    70.3 1056.43    90.4 1049.44
   115.2 1043.99   124.5 1040.81   136.7 1033.78   141.3    1029   145.9 1021.98
   156.9 1011.27   169.1 1000.14   195.9  978.18   203.3  976.45  223.62975.9574
   243.1  975.21     248 975.959   252.3  978.08     266   979.2   309.3  979.75
   326.5   984.5   338.4  990.36   356.6 1002.26   371.2 1013.35   385.4 1027.98
   392.3 1032.68   411.3 1039.81   427.2 1043.04   436.8  1046.1   471.8 1064.05
#Mann= 3 ,-1,0
       0      .1       0  223.62    .045       0     248      .1       0
Bank Sta=223.62,248
XS Rating Curve= 0 ,0
Exp/Cntr(USF)=0,0
Exp/Cntr=0.3,0.1

Type RM Length L Ch R = 1 ,3291    ,153.7,148.1,143.7
XS GIS Cut Line= 4
1643891.56068479493616.5888734261643679.74715771493663.496283513
1643590.07161167493629.6629727481643442.35340318 493558.11784026
#Sta/Elev= 30
       0 1073.85    14.6 1069.77    58.3 1051.71    88.6 1043.57    98.7 1037.95
   125.5  1019.4   162.7  996.12   175.9  988.75     186  984.16   196.1  980.47
   209.6  977.36   243.2  974.41  253.09971.8674   261.8  970.53  271.88971.8674
   279.3  973.34   293.4  978.66   318.1  984.11   329.3  988.48   336.4  989.75
   358.6  998.68   372.8  1005.3   397.9  1019.4   407.7 1026.72   416.5 1032.22
   424.9 1036.62   456.6 1049.76   464.8 1052.66   471.6 1054.02   476.9  1056.2
#Mann= 3 ,-1,0
       0      .1       0  253.09    .045       0  271.88      .1       0
Bank Sta=253.09,271.88
XS Rating Curve= 0 ,0
Exp/Cntr(USF)=0,0
Exp/Cntr=0.3,0.1

Type RM Length L Ch R = 1 ,3142    ,189.7,184.4,180.2
XS GIS Cut Line= 2
1643879.41678047493493.9160574561643446.30993512493526.320036761
#Sta/Elev= 30
       0 1075.31    18.6 1067.17    31.8 1058.33    48.2 1049.22    77.8 1038.25
    81.1 1036.09    87.7 1030.26      91 1026.85    97.7 1018.39   107.4 1010.63
     114 1004.48   127.2  993.69   143.6  983.16   160.1  974.94   176.5  972.03
   182.9 969.562     193  968.88  206.12969.5631   242.3  974.21   252.2  977.57
   265.4  980.03   281.8  985.48   299.5  992.82   317.8 1001.51   339.3 1014.66
   350.9 1023.11   360.8  1029.1   380.5 1038.82   409.7 1048.66   434.3 1059.39
#Mann= 3 ,-1,0
       0      .1       0   182.9    .045       0  206.12      .1       0
Bank Sta=182.9,206.12
XS Rating Curve= 0 ,0
Exp/Cntr(USF)=0,0
Exp/Cntr=0.3,0.1

Type RM Length L Ch R = 1 ,2958    ,144,139.1,132.9
XS GIS Cut Line= 3
1643787.86249752493251.1382675671643638.36380448493324.896394658
1643416.03508574493446.995872216
#Sta/Elev= 30
       0  1055.8      21 1046.31    56.2 1032.47    68.1 1025.13    79.6 1017.08
    90.5 1012.18   101.5 1003.07   116.2  995.97   151.7  972.28   156.6  969.68
   161.5  968.29   182.4  965.02  191.88 961.925   212.3  961.03  216.33 961.928
     222  967.91   224.4  969.65   241.3  972.29     261  978.84   272.2  982.91
   294.6  993.31   311.4  999.78   323.5 1007.96   335.8  1019.8   343.3 1025.52
   354.5 1032.24   369.5 1037.44     377 1041.26   403.2 1061.78   420.4 1071.14
#Mann= 3 ,-1,0
       0      .1       0  191.88    .045       0  216.33      .1       0
Bank Sta=191.88,216.33
XS Rating Curve= 0 ,0
Exp/Cntr(USF)=0,0
Exp/Cntr=0.3,0.1

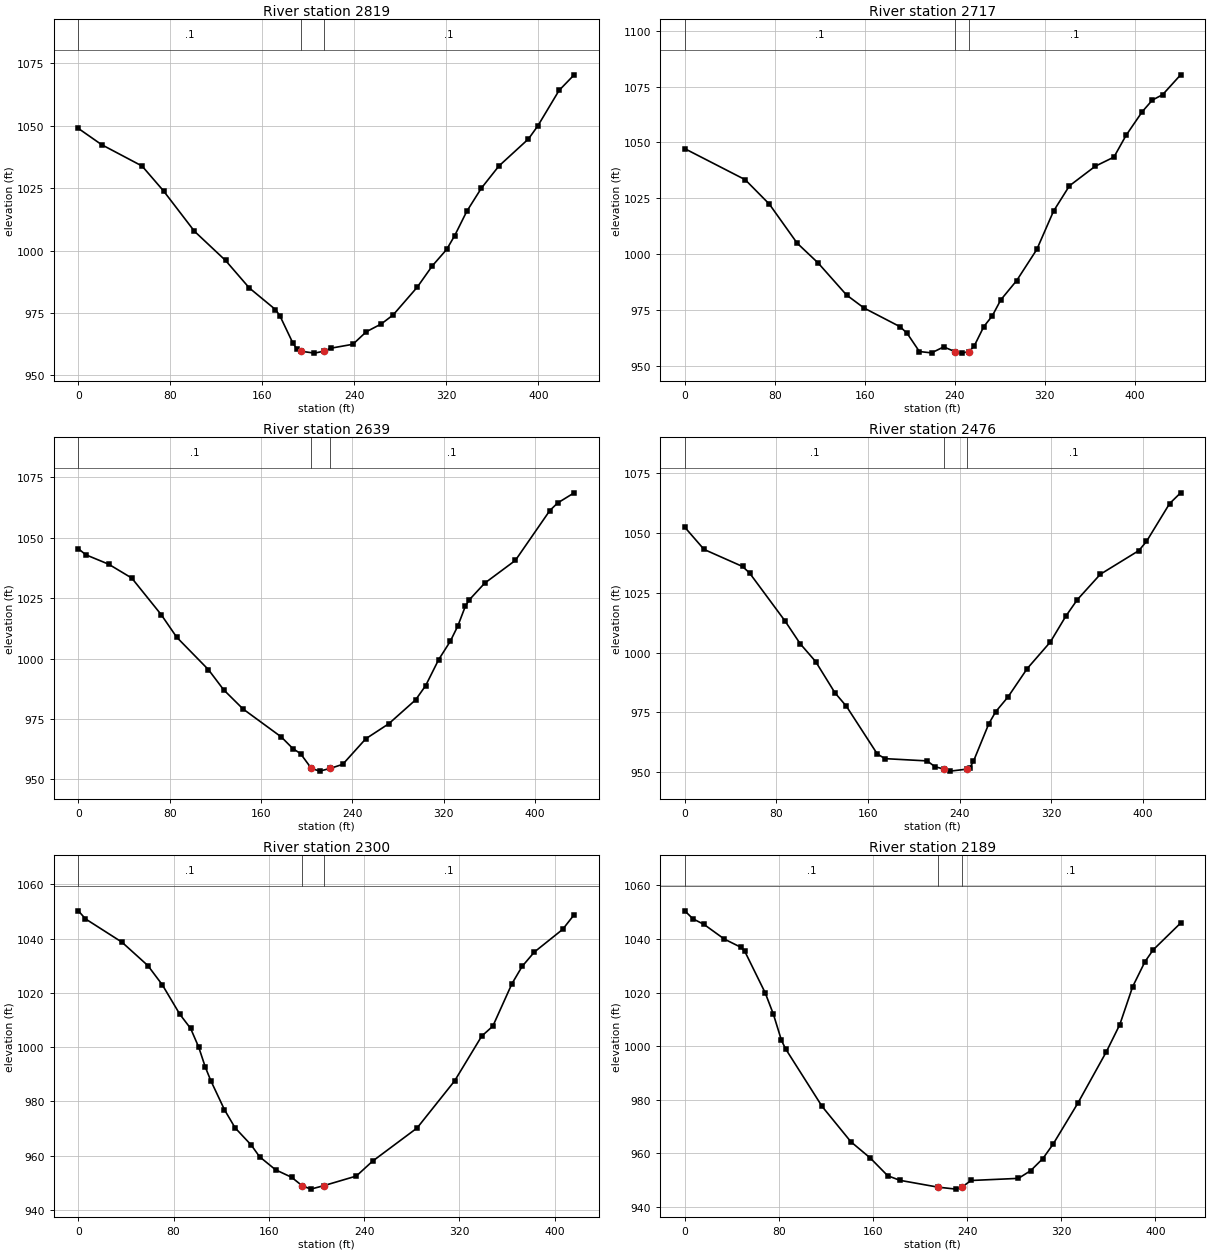
Type RM Length L Ch R = 1 ,2819    ,97.5,102.3,104.8
XS GIS Cut Line= 4
1643686.57358655493093.2131914061643554.58664645493195.167175075
1643520.60198523493256.0234288941643395.72811376493405.397870084
#Sta/Elev= 30
       0 1048.93    20.2 1042.43    55.4 1033.86    74.1 1023.88     101  1007.7
     128  996.02   148.7  984.99   171.4  976.35   175.2  973.93   186.5  962.98
   190.2  960.44  193.57 959.646   205.3  958.88  213.44 959.646   219.5  960.85
   238.8  962.43   250.4  967.43   263.5  970.59   273.8  974.19   294.7  985.29
   307.8  993.83   320.3 1000.42   327.3 1005.96   337.8 1015.69   350.5 1024.98
   365.8 1033.88   391.4 1044.68   399.5 1049.86   418.1 1064.17   431.2  1070.4
#Mann= 3 ,-1,0
       0      .1       0  193.57    .045       0  213.44      .1       0
Bank Sta=193.57,213.44
XS Rating Curve= 0 ,0
Exp/Cntr(USF)=0,0
Exp/Cntr=0.3,0.1

Type RM Length L Ch R = 1 ,2717    ,75,77.5,75.6
XS GIS Cut Line= 2
1643676.77437507493076.3800029281643275.38391239 493258.83021324
#Sta/Elev= 30
       0  1047.2    53.7  1033.3    75.2 1022.33    99.9 1004.85   118.5     996
   143.8  981.62   159.4  975.77   191.6  967.34   197.8  964.36   208.6  956.26
   219.4  955.66   230.2  958.34  240.42956.1868   246.1  955.55  252.64956.2036
   257.2   958.6   265.9  967.45   273.4  972.23     281  979.44   295.1  988.07
     313 1002.01   327.9 1019.21     342 1030.54     365 1039.34   381.6 1043.43
   392.4 1053.19   406.8  1063.8   415.8 1069.01   424.9 1071.41   440.9 1080.31
#Mann= 3 ,-1,0
       0      .1       0  240.42    .045       0  252.64      .1       0
Bank Sta=240.42,252.64
XS Rating Curve= 0 ,0
Exp/Cntr(USF)=0,0
Exp/Cntr=0.3,0.1

Type RM Length L Ch R = 1 ,2639    ,162.7,163.1,163
XS GIS Cut Line= 2
1643667.06752068 493060.12146093 1643242.9550856493153.795615882
#Sta/Elev= 30
       0 1045.52     6.5    1043    26.6 1039.08    46.8 1033.35    72.5 1018.26
    86.2 1008.84     114  995.41   127.3  987.09   144.2  979.18   177.8  967.56
   187.9  962.76   194.6  960.68  204.12954.5455   211.4  953.42  220.68954.5485
   231.6  956.24   251.8  966.82   271.9  973.03   295.4  982.92   304.2  988.79
   315.6  999.58   325.7 1007.09   332.4 1013.51   339.1 1021.82   342.5 1024.36
   355.9 1031.22   382.8 1040.66     413 1061.31   419.8 1064.43   434.3 1068.64
#Mann= 3 ,-1,0
       0      .1       0  204.12    .045       0  220.68      .1       0
Bank Sta=204.12,220.68
XS Rating Curve= 0 ,0
Exp/Cntr(USF)=0,0
Exp/Cntr=0.3,0.1

Type RM Length L Ch R = 1 ,2476    ,176.2,176.1,175.6
XS GIS Cut Line= 2
1643631.24971945492912.2251118691643208.41730655493004.695004034
#Sta/Elev= 30
       0 1052.41    16.8 1043.13    50.4 1035.99    56.5 1033.28    87.4 1013.25
   100.8 1003.62   114.2  996.22     131  983.18   141.1  977.48     168  957.56
   174.7   955.6   211.6  954.64   218.3  952.22   226.3951.2233   231.8  950.37
  246.44951.2226   248.6  951.62   251.9  954.41   265.4  970.23   271.4  975.24
   282.1  981.39   298.9  993.28   319.1 1004.41   332.5 1015.13   342.6 1022.09
   362.7 1032.73   396.3 1042.63     403 1046.47   423.2 1062.32   432.8 1066.81
#Mann= 3 ,-1,0
       0      .1       0   226.3    .045       0  246.44      .1       0
Bank Sta=226.3,246.44
XS Rating Curve= 0 ,0
Exp/Cntr(USF)=0,0
Exp/Cntr=0.3,0.1

Type RM Length L Ch R = 1 ,2300    ,109.8,110.9,109.1
XS GIS Cut Line= 2
1643584.51588803 492743.250191641643182.16977617492850.059912687
#Sta/Elev= 30
       0 1050.21       6 1047.24    36.6 1038.66    58.4 1030.01    70.5 1022.94
    85.2 1012.09    94.3 1006.83   101.1  999.91   106.6   992.6   111.2  987.62
   122.7  976.88   131.6  970.22   145.2  963.84   152.2  959.54   165.6  954.74
   179.1  951.97  187.84 948.881   195.2  947.61  206.04948.8815   233.4  952.43
     247   957.9   284.4  970.14   315.9  987.49   338.7 1004.03     348 1007.68
   364.1 1023.37   372.6 1029.71   382.9 1035.03   406.6 1043.35   416.3 1048.78
#Mann= 3 ,-1,0
       0      .1       0  187.84    .045       0  206.04      .1       0
Bank Sta=187.84,206.04
XS Rating Curve= 0 ,0
Exp/Cntr(USF)=0,0
Exp/Cntr=0.3,0.1

Type RM Length L Ch R = 1 ,2189    ,155,156.7,156.5
XS GIS Cut Line= 2
 1643548.1449408492629.380196422 1643149.7531584492767.114822871
#Sta/Elev= 30
       0 1050.45     6.9 1047.47    16.3 1045.39    33.6 1039.92    47.5  1036.9
      51 1035.34    68.3 1019.93    75.3 1011.93    82.2 1002.13    85.7  998.99
   116.7  977.55   141.2  964.36   157.6  958.33   172.5   951.7   182.9  949.99
   215.1  947.46   230.5  946.71  235.47947.4447   243.4  949.93   283.6  950.72
     294  953.58   304.4  958.11     313  963.41   334.2   978.8   358.4  997.94
   369.8 1008.05   380.7 1022.15   391.2  1031.5   398.2 1035.92   421.5 1045.89
#Mann= 3 ,-1,0
       0      .1       0   215.1    .045       0  235.47      .1       0
Bank Sta=215.1,235.47
XS Rating Curve= 0 ,0
Exp/Cntr(USF)=0,0
Exp/Cntr=0.3,0.1

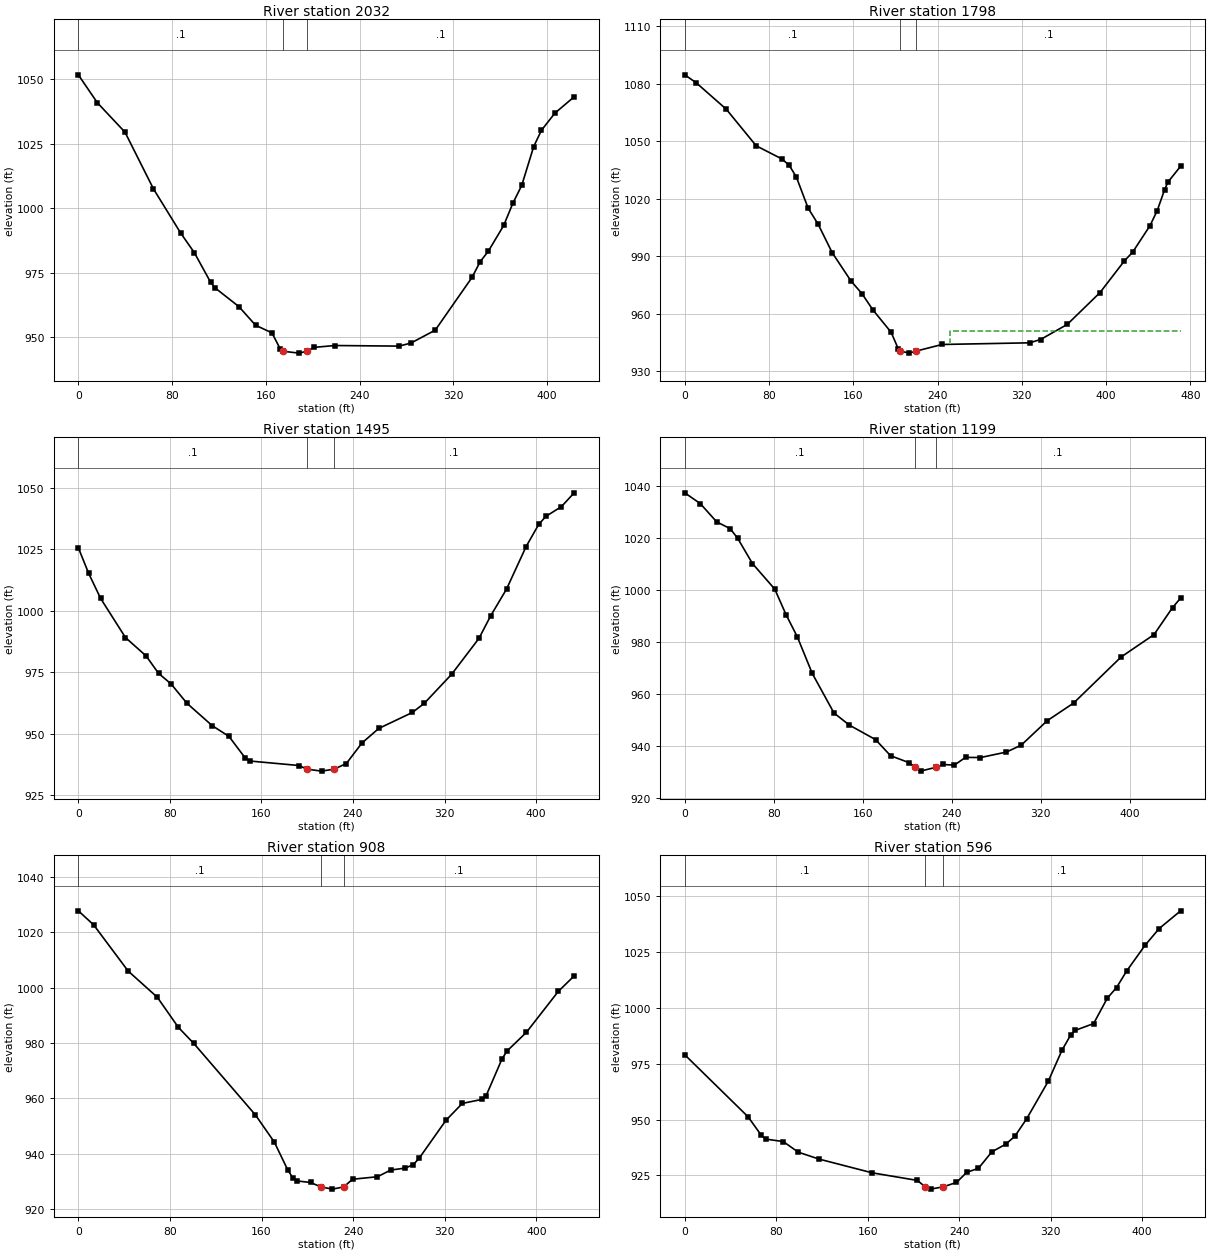
Type RM Length L Ch R = 1 ,2032    ,230.2,234.1,230.6
XS GIS Cut Line= 2
1643488.19800593492497.2961085631643089.86616275492639.557481125
#Sta/Elev= 30
       0  1051.7    16.3 1040.84    39.8 1029.47    64.1 1007.48    87.3  990.37
      99  982.73   112.9  971.25   116.4  969.19     137  961.83   151.2  954.62
   165.2  951.66   172.1  945.55  174.49944.5418   188.3  943.81  194.98944.5403
   201.2  946.05   219.1  946.76   273.5  946.53   283.6  947.68   304.5  952.72
   335.9  973.19   342.8  979.25   349.8  983.34   362.9  993.31   370.7  1001.9
   378.3 1008.87   388.5 1023.91   395.1  1030.2   406.5 1036.82     423 1043.18
#Mann= 3 ,-1,0
       0      .1       0  174.49    .045       0  194.98      .1       0
Bank Sta=174.49,194.98
XS Rating Curve= 0 ,0
Exp/Cntr(USF)=0,0
Exp/Cntr=0.3,0.1

Type RM Length L Ch R = 1 ,1798    ,297.9,303.3,301.7
XS GIS Cut Line= 2
1643482.22143367 492360.646810011643036.04367147492510.789949022
#Sta/Elev= 30
       0 1084.57    10.9  1080.4    39.4 1066.61    67.8 1047.53      92 1040.73
      99 1037.48   105.9 1031.27   117.1 1015.01   126.7 1006.51   139.9  991.81
   157.8  976.98   168.2  970.41   178.6   961.9   195.9  950.24   202.8  941.44
  204.74940.4091   213.2  939.34   219.7 940.412   244.4  943.86   327.4  944.72
   337.8  946.45   363.1   954.3   394.2   970.9   417.4  987.47   425.3  992.06
   441.7 1005.84   448.6 1013.74   455.5 1024.53   458.8 1028.63   470.8 1036.88
#Mann= 3 ,-1,0
       0      .1       0  204.74    .045       0   219.7      .1       0
#XS Ineff= 2 , 0
                          251.62          950.67
Permanent Ineff=
       F       F
Bank Sta=204.74,219.7
XS Rating Curve= 0 ,0
Exp/Cntr(USF)=0,0
Exp/Cntr=0.3,0.1

Type RM Length L Ch R = 1 ,1495    ,289.2,295.9,301.2
XS GIS Cut Line= 6
  1643314.258515492122.6420366761643234.75244042492159.431661248
1643166.62101501 492190.912241341643070.34561701492224.258959427
1642995.01013775 492246.107997091642908.70978542492272.604335174
#Sta/Elev= 30
       0 1025.57       9 1015.18    19.5 1004.96    41.2  989.07    59.3  981.57
    70.1  974.53      81  970.25    94.9  962.37   117.1  953.23   131.6  948.92
     146  940.03   149.6  938.91   192.9  937.07  199.76935.5892   212.6  934.79
  223.51935.5903   234.2  937.87   247.9  946.24   262.5  952.12     292  958.65
   302.3  962.34   326.2  974.13   350.1  988.74   360.4  997.96   374.2 1008.76
   391.3 1026.04   402.3 1035.03   408.5 1038.29   422.2  1042.3   433.3 1047.89
#Mann= 3 ,-1,0
       0      .1       0  199.76    .045       0  223.51      .1       0
Bank Sta=199.76,223.51
XS Rating Curve= 0 ,0
Exp/Cntr(USF)=0,0
Exp/Cntr=0.3,0.1

Type RM Length L Ch R = 1 ,1199    ,297.2,290.7,276.2
XS GIS Cut Line= 6
1643326.59182367491979.4530185911643240.93123384491961.607581839
1643167.50749618491946.3113525961643070.01917408491923.692303345
1642990.14531809491909.4944970911642889.08384043491922.670979917
#Sta/Elev= 30
       0 1037.44    13.9  1033.3    28.7 1026.26    40.7 1023.69    47.4 1020.05
    60.8 1010.25    80.9 1000.38      91  990.59   101.1  982.09   114.5  968.03
   134.1  952.76   147.9  948.13   171.5  942.53   184.9  936.36   201.8  933.64
  206.65931.9022   211.9  930.43  225.64931.9038   232.1  932.99   242.2  932.73
   252.3  935.72   265.7  935.65   289.1  937.77   302.4  940.44   325.7  949.82
   349.4  956.59     392  974.28   421.7  982.93   438.3   993.3   445.6  996.97
#Mann= 3 ,-1,0
       0      .1       0  206.65    .045       0  225.64      .1       0
Bank Sta=206.65,225.64
XS Rating Curve= 0 ,0
Exp/Cntr(USF)=0,0
Exp/Cntr=0.3,0.1

Type RM Length L Ch R = 1 ,908     ,305.9,312,302.1
XS GIS Cut Line= 6
1643135.45506684491549.4341935961643071.62251735 491612.85335809
1643014.24631976491666.2223458441642947.09127034491742.433807582
1642907.22947343491805.9635361731642847.62591809491870.905335426
#Sta/Elev= 30
       0 1027.73    13.4 1022.65    43.5 1005.99      69  996.52    87.4  985.63
   100.9  979.82   154.7  954.02   171.2  944.22   182.8  934.26   187.4  931.24
   191.4  930.17   202.8  929.63  211.82928.0458     222  927.23  231.89928.0431
   239.5   930.8   261.3   931.7   272.9  934.13   285.6  934.82   292.6  936.09
   297.6  938.31   321.1  952.07   335.4  958.18   352.4  959.62   356.2  960.96
   370.2  974.36   374.6  977.16   391.4  983.86   419.2  998.61   433.1 1004.23
#Mann= 3 ,-1,0
       0      .1       0  211.82    .045       0  231.89      .1       0
Bank Sta=211.82,231.89
XS Rating Curve= 0 ,0
Exp/Cntr(USF)=0,0
Exp/Cntr=0.3,0.1

Type RM Length L Ch R = 1 ,596     ,294.1,291.9,293.1
XS GIS Cut Line= 6
1642986.07675667491354.6944255831642910.18616043491401.342626259
1642855.83423501491453.1351735891642779.97086968491521.249866754
1642717.13208459491567.0388171671642643.91897643491618.863516673
#Sta/Elev= 30
       0  979.04    55.3  951.29    66.9  942.99    70.7  941.29    86.1  940.18
    99.2  935.43   117.3  932.34   163.9  926.17   203.4  922.77  210.24 919.886
     215  918.87  225.81919.8871   237.6  921.85   246.5  926.39   256.8  928.19
   268.5  935.57   280.5  938.95   288.6  942.52     299  950.41   317.8  967.16
   329.9  981.14   337.3  987.76   341.2  989.94   357.5  993.03   369.5 1004.42
   377.6 1009.19   386.4 1016.58   402.4 1028.04   414.8 1035.58   433.6 1043.54
#Mann= 3 ,-1,0
       0      .1       0  210.24    .045       0  225.81      .1       0
Bank Sta=210.24,225.81
XS Rating Curve= 0 ,0
Exp/Cntr(USF)=0,0
Exp/Cntr=0.3,0.1

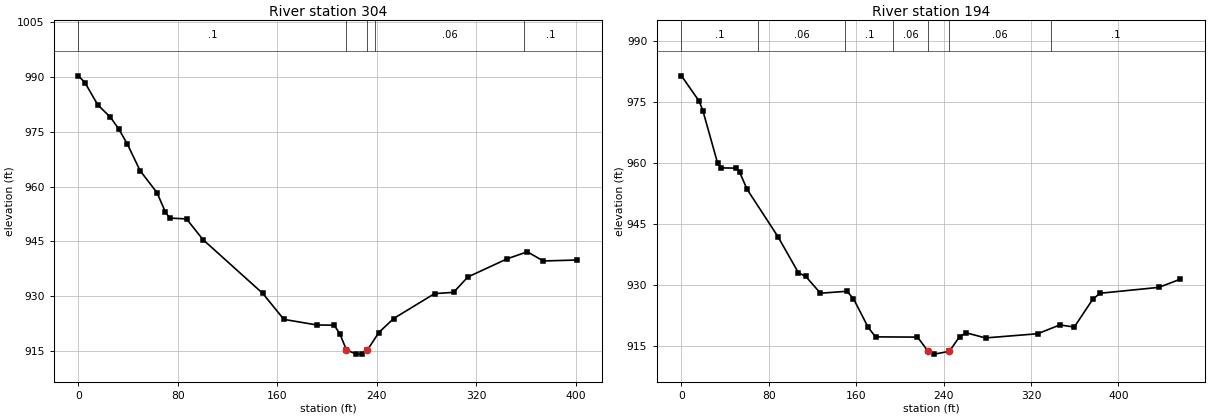
Type RM Length L Ch R = 1 ,304     ,109.1,110,108
XS GIS Cut Line= 3
1642953.86728641491139.0382893931642781.66673794491186.293214638
1642618.48751987491338.054004245
#Sta/Elev= 30
       0  990.37     5.3  988.44    15.5  982.42    25.7  979.01    32.5  975.73
    39.3  971.67    49.5  964.39    63.1  958.36    69.9  953.03    73.3  951.37
    86.9  951.13   100.1  945.47   148.2  930.72   165.2  923.59   191.6  922.06
   205.7  921.99   210.2  919.64  215.58915.1889   223.6  914.06   228.1  914.12
  232.38915.1866   241.6  919.99   253.5  923.82   286.4  930.65   301.7     931
   313.2  935.21   344.8  940.19     361  942.12   373.9   939.6   401.4  939.87
#Mann= 5 ,-1,0
       0      .1       0  215.58    .045       0  232.38      .1       0
  238.57     .06       0  358.57      .1       0
Bank Sta=215.58,232.38
XS Rating Curve= 0 ,0
Exp/Cntr(USF)=0,0
Exp/Cntr=0.3,0.1

Type RM Length L Ch R = 1 ,194     ,,,
XS GIS Cut Line= 4
1642899.11355788491070.4350404481642709.84164471491112.710817654
1642632.55202068 491196.972558661642600.01044135491342.004055305
#Sta/Elev= 30
       0  981.45    16.3  975.17    19.7  972.78    33.1  959.95    36.5  958.78
    49.9  958.71    53.3   957.7      60  953.54    88.3  941.86   107.1  932.95
   113.8  932.04   127.3  927.91   151.5  928.39   157.5  926.56     171  919.48
   177.7  917.16   216.1   917.1   225.9 913.595   231.4  912.91  245.27913.5953
   254.6  917.19   260.6  918.16   278.4   916.9   326.1  917.93   346.5   920.1
   359.7  919.58   376.5  926.39   383.2   927.9   437.1  929.35   456.9  931.38
#Mann= 7 ,-1,0
       0      .1       0      70     .06       0     150      .1       0
  193.94     .06       0   225.9    .045       0  245.27     .06       0
  338.28      .1       0
Bank Sta=225.9,245.27
XS Rating Curve= 0 ,0
Exp/Cntr(USF)=0,0
Exp/Cntr=0.3,0.1
LCMann Table=0

Chan Stop Cuts=-1
Use User Specified Reach Order=0
Composite Channel Slope=5